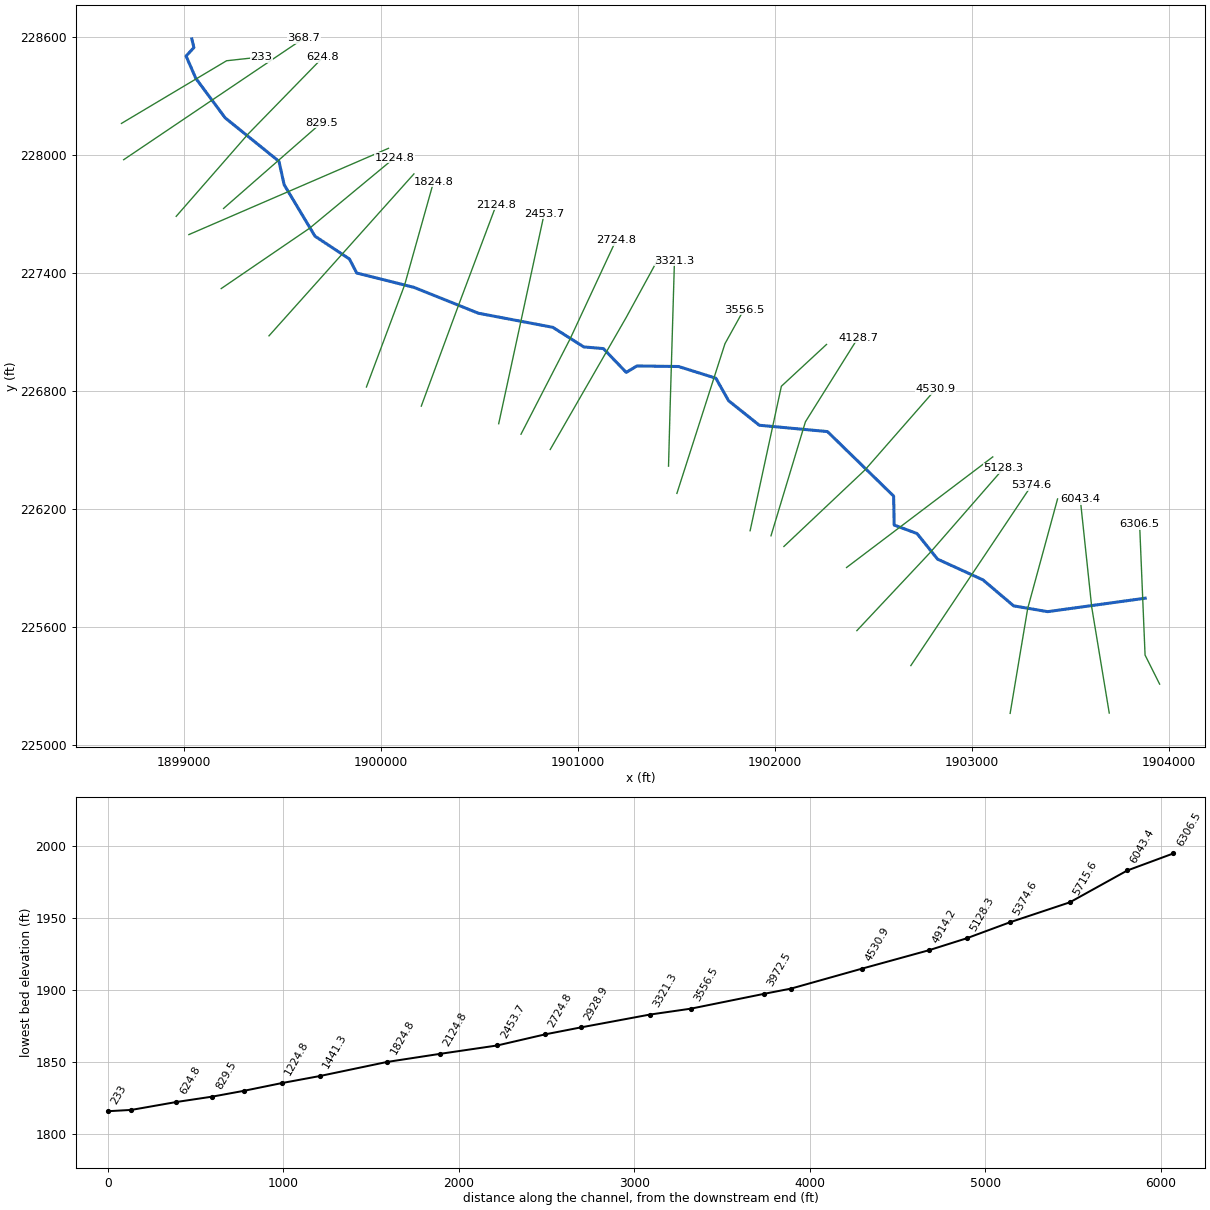
--- PnsCrk.prj (project) ---

Proj Title=PnsCrk
Current Plan=p01
Default Exp/Contr=0,0
English Units
Geom File=g01
Flow File=f01
Plan File=p01
BEGIN DESCRIPTION:
END DESCRIPTION:
DSS Export Rating Curves= 0
DSS Export Rating Curve Sorted= 0
DSS Export Volume Flow Curves= 0
DXF OffsetX= 0
DXF OffsetY= 0
DXF ScaleX= 0
DXF ScaleY= 0

--- PnsCrk.p01 (plan) ---

Plan Title=Floodplain
Program Version=4.00
Geom File=g01
Flow File=f01
K Sum by GR=0
Std Step Tol=0.01
Critical Tol=0.01
Num of Std Step Trials=20
Max Error Tol=0.3
Flow Tol Ratio=0.001
Split Flow NTrial=30
Split Flow Tol=0.02
Split Flow Ratio=0.02
Log Output Level=0
Friction Slope Method=1
Unsteady Friction Slope Method=2
Unsteady Bridges Friction Slope Method=1
Global Log Level=0
CheckData=False
Run HTab=0
Run UNet=0
Run PostProcess=0
UNET Theta=0
UNET Theta Warmup=0
UNET ZTol=0
UNET ZSATol=0
UNET MxIter=0
UNET MaxInSteps=0
UNET DtIC=0
UNET DtMin=0
UNET MaxCRTS=0
UNET WFStab=0
UNET SFStab=0
UNET WFX=0
UNET SFX=0
UNET DSS MLevel=0
UNET DZMax Abort=0
UNET Convert EG Bridges=0
UNET Use Existing IB Tables=0
UNET Froude Limit=0
UNET Froude Power=0
Write IC File=0
Echo Input=False
Echo Output=False
Write Detailed=0

--- PnsCrk.f01 (steady flow) ---

Flow Title=NFF Regression Equation
Program Version=4.00
Number of Profiles=1
Profile Names=P100yr
River Rch & RM=PnsCrk,Main      ,6306.5
882.6886
River Rch & RM=PnsCrk,Main      ,4530.9
953.4482
River Rch & RM=PnsCrk,Main      ,3556.5
1046.799
River Rch & RM=PnsCrk,Main      ,233
1146.894
Boundary for River Rch & Prof#=PnsCrk,Main      ,1
Up Type=0
Dn Type=3
Dn Slope=0.015494

--- PnsCrk.g01 (geometry) ---

Geom Title=USGS 3m DEM
Program Version=4.10

River Reach=PnsCrk          ,Main
Reach XY= 30
     1903879.316      225746.823     1903384.354      225678.387
     1903211.497      225707.878     1903056.113      225839.915
     1902825.562      225945.429     1902721.361      226075.689
     1902605.434      226118.677     1902602.574      226266.218
     1902266.783      226594.123     1901920.871      226626.384
     1901764.935      226751.141     1901700.341      226865.576
     1901511.306      226924.998     1901299.798      226927.886
     1901245.583      226895.047     1901129.658      227016.189
     1901029.926      227024.742     1900873.057       227124.31
     1900495.316      227195.963     1900168.377      227327.532
     1899877.907      227400.485     1899840.708      227471.774
     1899665.596      227588.061     1899509.297      227849.881
     1899483.249      227968.414     1899209.719      228189.859
     1899061.233      228390.458     1899011.739      228503.782
     1899051.332      228547.108     1899040.879      228591.161

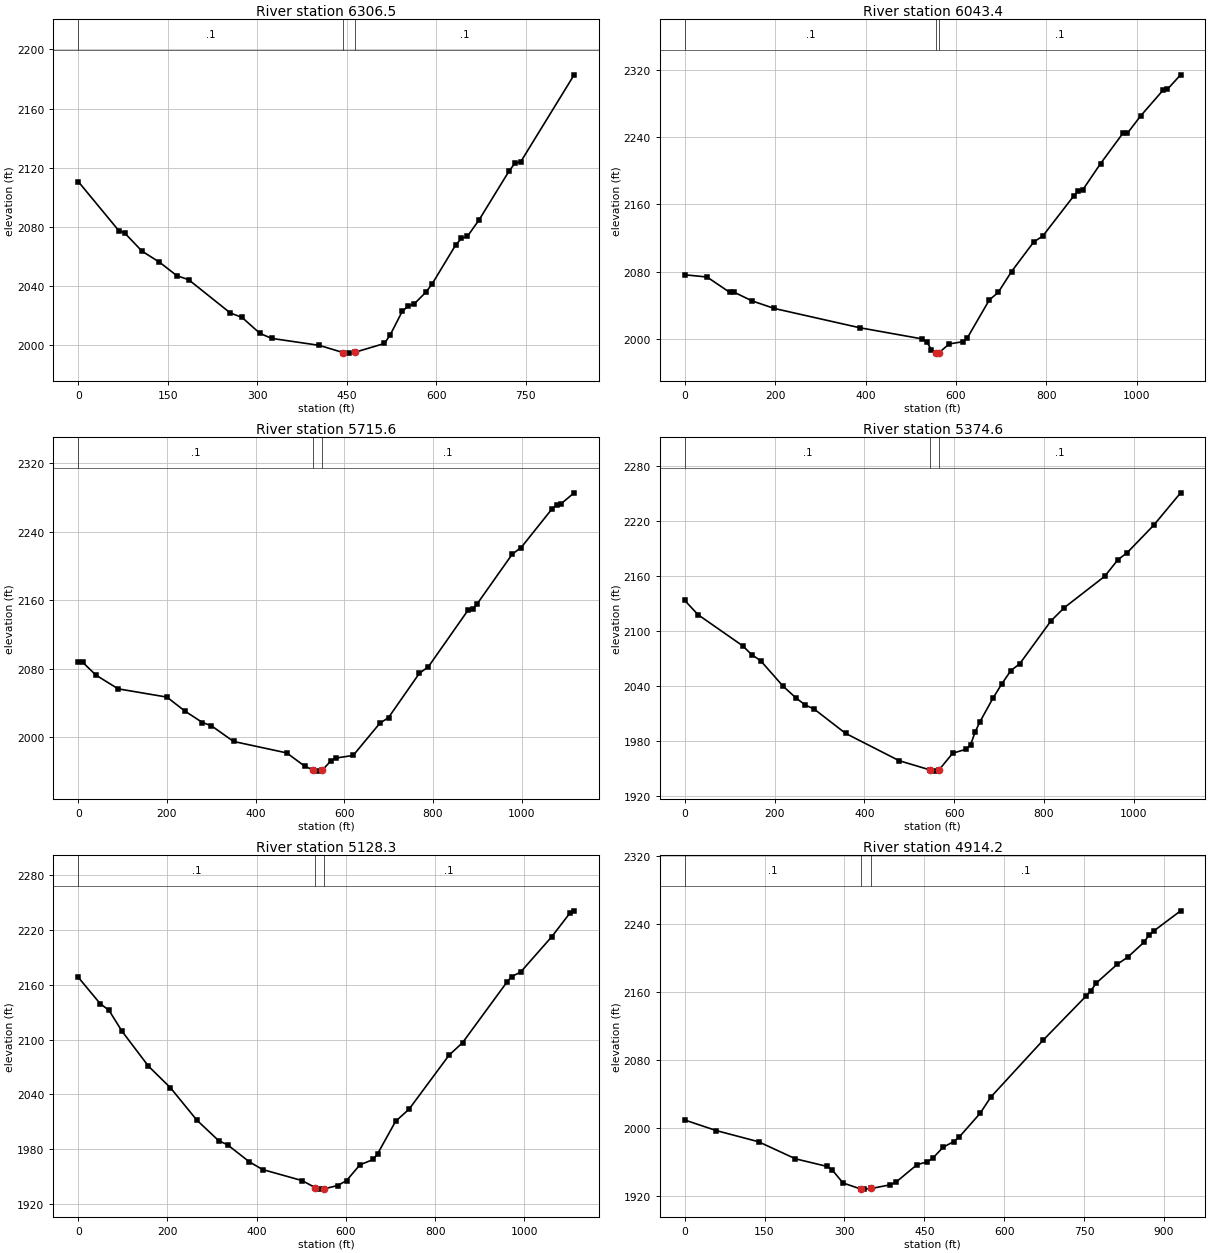
Type RM Length L Ch R = 1 ,6306.5  ,260.4,263,264.6
XS GIS Cut Line= 3
     1903952.555      225309.784     1903878.652      225457.591
     1903850.938      226122.719
#Sta/Elev= 30
       0 2110.67      68 2077.46    77.8 2075.91   106.9 2063.59   136.1 2056.18
   165.2 2047.06   185.1  2044.3   254.7 2021.88   274.6  2018.8   304.4 2008.06
   324.2 2004.65   403.7 1999.97   444.4 1995.02   453.4  1994.7   464.4 1995.37
     513 2001.21   522.9 2007.07   542.8 2022.83   552.8 2026.52   562.7 2027.84
   582.6  2035.9   592.5 2041.13   632.2 2067.58   642.2 2072.26   652.1 2073.58
     672 2084.92   721.7 2117.58   731.6 2122.97   741.5    2124     831 2182.76
#Mann= 3 , 0 , 0
       0      .1       0   444.4    .045       0   464.4      .1       0
Bank Sta=444.4,464.4
XS Rating Curve= 0 ,0
Exp/Cntr=0.3,0.1

Type RM Length L Ch R = 1 ,6043.4  ,335.7,327.6,318.3
XS GIS Cut Line= 3
     1903696.816      225162.773     1903607.917      225701.227
     1903549.971      226249.254
#Sta/Elev= 30
       0 2076.15    49.6 2073.46    99.2 2055.38   109.2 2055.42   148.8 2045.09
   198.4 2036.01     387  2013.1   525.9 1999.71   535.8 1995.91   545.7 1986.86
   555.6 1982.85   562.1 1983.27   585.1 1993.79   614.6 1996.39   624.5 2000.41
   673.7 2046.17   693.4 2055.15   722.9 2080.01   772.1 2115.35   791.8 2122.16
   860.6 2170.13   870.5 2175.44   880.3 2177.23   919.7 2208.53   968.9 2244.48
   978.7  2244.4  1008.3 2265.27  1057.5  2295.7  1067.3 2296.88  1096.8 2314.25
#Mann= 3 , 0 , 0
       0      .1       0   555.6    .045       0   562.1      .1       0
Bank Sta=555.6,562.1
XS Rating Curve= 0 ,0
Exp/Cntr=0.3,0.1

Type RM Length L Ch R = 1 ,5715.6  ,351.8,341.1,332.8
XS GIS Cut Line= 3
     1903193.893      225161.082     1903282.854      225694.005
     1903434.622      226251.752
#Sta/Elev= 30
       0 2088.42      10 2087.64      40 2072.65      90 2056.67   200.1 2047.02
   240.1 2030.92   280.2 2017.38   300.2 2013.67   350.2 1995.35   470.3 1981.98
   510.3  1966.7   530.3  1961.8   540.3 1960.76   550.3 1961.83   570.2 1972.99
   580.2 1975.93     620 1979.04   679.8 2016.35   699.8 2023.24   769.5 2074.94
   789.4 2082.26   879.1 2148.37   889.1 2149.62   899.1 2155.34   978.8 2213.68
   998.7  2221.3  1068.5 2266.44  1078.5 2270.93  1088.4 2272.18  1118.3  2285.1
#Mann= 3 , 0 , 0
       0      .1       0   530.3    .045       0   550.3      .1       0
Bank Sta=530.3,550.3
XS Rating Curve= 0 ,0
Exp/Cntr=0.3,0.1

Type RM Length L Ch R = 1 ,5374.6  ,250.4,246.3,243.1
XS GIS Cut Line= 2
     1902689.902      225404.028     1903303.392      226322.157
#Sta/Elev= 30
       0 2133.02    29.8  2117.4   129.3 2083.46   149.2 2073.87   169.1 2067.26
   218.9 2039.58   248.7 2026.28   268.6    2019   288.5 2014.47   358.1 1988.12
   477.5  1958.3     547 1948.13   557.1 1946.92     567 1948.69   596.9 1966.51
   626.7 1970.76   636.7 1975.77   646.6 1989.46   656.6    2000   686.4 2026.46
   706.3 2042.15   726.2 2056.47   746.1 2063.99   815.7 2110.77   845.6 2125.23
   935.1 2159.23     965 2177.54   984.9 2184.84  1044.5 2215.06  1104.2 2250.24
#Mann= 3 , 0 , 0
       0      .1       0     547    .045       0     567      .1       0
Bank Sta=547,567
XS Rating Curve= 0 ,0
Exp/Cntr=0.3,0.1

Type RM Length L Ch R = 1 ,5128.3  ,220.8,214.1,205.8
XS GIS Cut Line= 3
     1902416.118      225581.961     1902786.244       225977.14
     1903160.672      226407.375
#Sta/Elev= 30
       0 2168.34    49.2 2139.38    68.9  2132.1    98.4 2108.91   157.5 2070.74
   206.7 2047.08   265.8 2011.61     315 1988.93   334.7 1984.51   383.9 1965.68
   413.5  1957.3   502.1 1945.16   531.4 1937.45   541.4 1935.82   551.4 1936.14
   581.5 1939.76   601.5 1945.16   631.5 1962.43   661.5 1968.41   671.5 1974.91
   711.6 2010.29   741.6 2023.49   831.6 2082.96   861.6  2096.5   961.7 2163.39
   971.7 2169.14   991.7 2173.93  1061.8 2212.93  1101.8 2238.42  1111.8 2241.22
#Mann= 3 , 0 , 0
       0      .1       0   531.4    .045       0   551.4      .1       0
Bank Sta=531.4,551.4
XS Rating Curve= 0 ,0
Exp/Cntr=0.3,0.1

Type RM Length L Ch R = 1 ,4914.2  ,379.1,383.3,390.7
XS GIS Cut Line= 2
     1902363.637      225902.857      1903105.76      226465.428
#Sta/Elev= 30
       0 2008.99    59.4  1996.5   138.7 1983.36     208 1963.27   267.5 1954.28
   277.4 1949.92   297.2 1934.86   330.3 1927.75   336.8 1927.57   350.3 1928.33
   386.4  1932.7   396.3 1935.54   435.9 1956.18   455.7 1959.85   465.6 1963.82
   485.4 1976.96   505.2 1983.56   515.2 1988.72   554.8 2016.88   574.6 2035.84
   673.7 2103.39   752.9 2154.42   762.8 2161.17   772.7 2170.17   812.4 2192.45
   832.2 2200.87   861.9 2218.01   871.8 2226.44   881.7 2231.97   931.2 2255.28
#Mann= 3 , 0 , 0
       0      .1       0   330.3    .045       0   350.3      .1       0
Bank Sta=330.3,350.3
XS Rating Curve= 0 ,0
Exp/Cntr=0.3,0.1

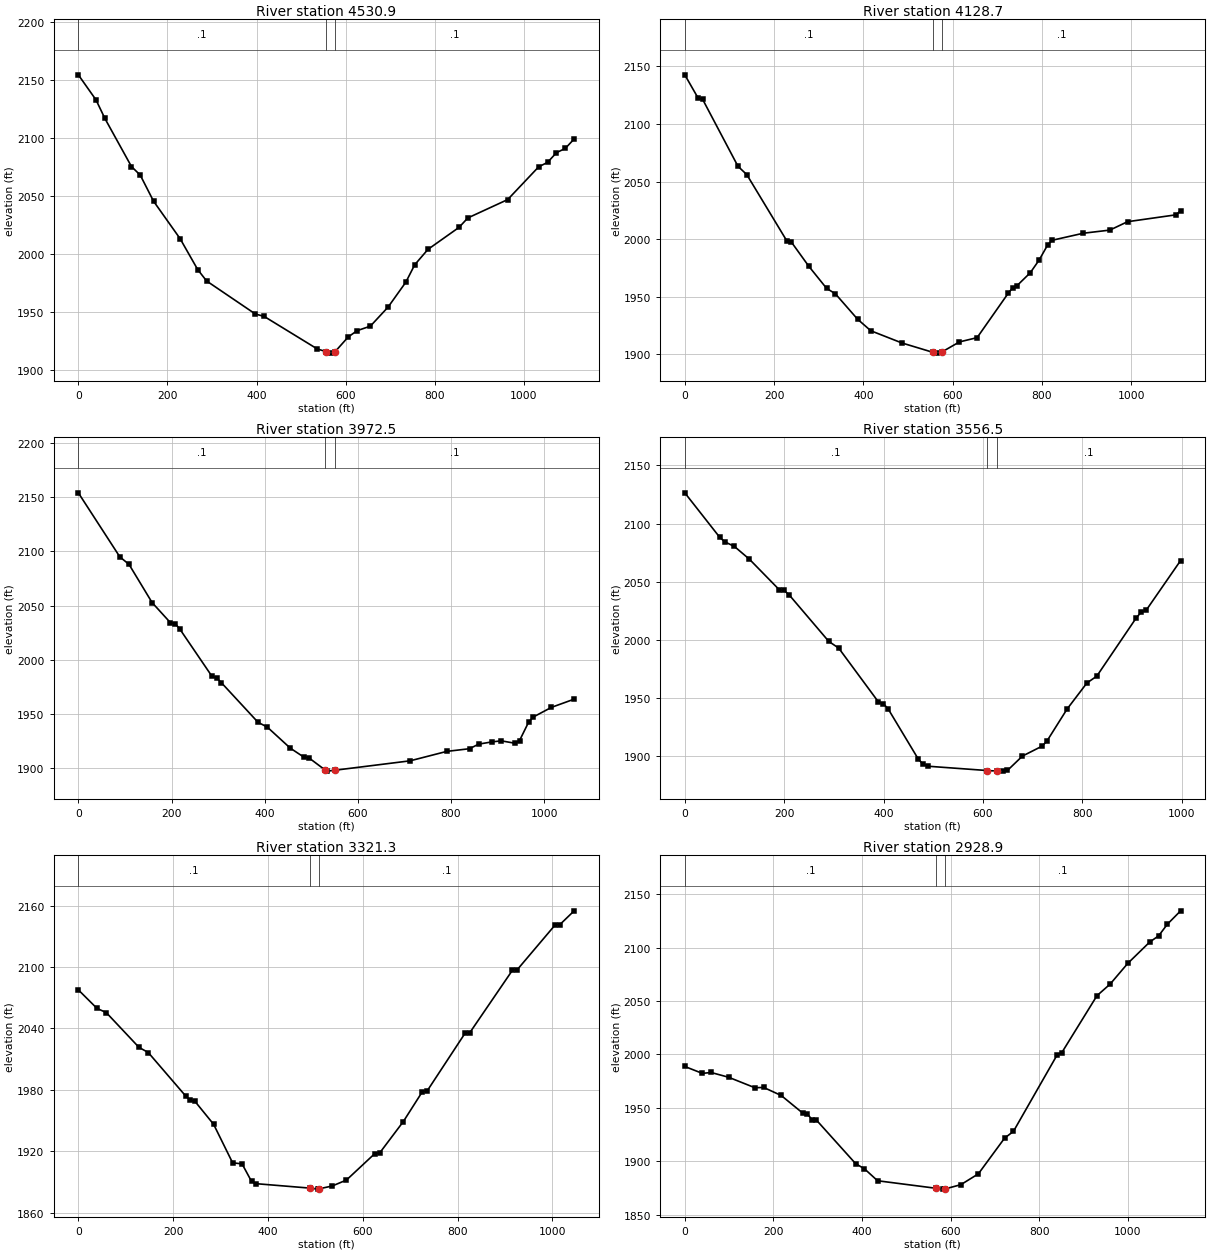
Type RM Length L Ch R = 1 ,4530.9  ,389.1,402.2,412.8
XS GIS Cut Line= 3
      1902045.74      226009.894     1902456.934      226398.802
     1902816.713      226810.566
#Sta/Elev= 30
       0 2154.55    39.7 2132.93    59.6 2116.95   119.2 2075.54     139  2068.1
   168.8 2045.66   228.4 2013.37   268.1 1986.61     288 1976.87   397.2 1948.46
     417 1946.38   536.2 1918.34     556 1916.03     566 1914.73     576 1915.88
   605.7 1928.65   625.6 1934.08   655.4 1937.97   695.2 1954.41     735 1975.86
   754.9 1990.84   784.7 2004.14   854.3 2023.06   874.2 2031.23   963.6 2047.05
  1033.2 2075.29  1053.1  2079.1    1073 2087.44  1092.9 2091.15  1112.8 2099.27
#Mann= 3 , 0 , 0
       0      .1       0     556    .045       0     576      .1       0
Bank Sta=556,576
XS Rating Curve= 0 ,0
Exp/Cntr=0.3,0.1

Type RM Length L Ch R = 1 ,4128.7  ,154.1,156.2,158.2
XS GIS Cut Line= 3
     1901980.229      226064.209     1902154.861      226643.736
      1902422.76      227072.374
#Sta/Elev= 30
       0 2142.76    29.8 2122.56    39.7 2121.64   119.1  2063.3   138.9 2056.05
   228.2  1998.7   238.1  1997.8   277.8 1976.42   317.5  1957.3   337.4 1952.48
     387 1930.45   416.7 1920.39   486.2 1909.81   556.8 1901.54   565.6 1900.96
   576.8 1902.16   615.2  1910.7   654.8 1914.41   724.2  1952.8   734.1  1957.6
     744 1959.51   773.8 1970.75   793.6 1981.75   813.4 1995.32   823.3 1999.05
   892.7 2005.13   952.2 2007.86   991.8 2015.15  1100.8 2021.15  1110.7 2024.86
#Mann= 3 , 0 , 0
       0      .1       0   556.8    .045       0   576.8      .1       0
Bank Sta=556.8,576.8
XS Rating Curve= 0 ,0
Exp/Cntr=0.3,0.1

Type RM Length L Ch R = 1 ,3972.5  ,418.3,415.6,413
XS GIS Cut Line= 3
     1901874.251      226089.917     1902032.921      226824.799
     1902262.021       227037.27
#Sta/Elev= 30
       0 2153.99      89 2094.97   108.8 2087.96   158.3 2052.76   197.8 2034.13
   207.7 2033.43   217.6 2028.46   286.9 1984.68   296.8 1983.23   306.7 1978.99
   385.8 1942.26   405.6 1937.88     455 1918.44   484.7    1910   494.6  1909.6
   530.2 1898.14   534.2 1897.25   550.2 1898.05   712.2 1906.76   790.9 1915.46
   839.7 1917.93   859.2 1922.14   888.5 1924.27     908 1925.18   937.3 1922.97
   947.1 1925.46   966.6 1942.49   976.4 1947.13  1015.4 1956.05  1064.3 1963.65
#Mann= 3 , 0 , 0
       0      .1       0   530.2    .045       0   550.2      .1       0
Bank Sta=530.2,550.2
XS Rating Curve= 0 ,0
Exp/Cntr=0.3,0.1

Type RM Length L Ch R = 1 ,3556.5  ,226,235.2,243.4
XS GIS Cut Line= 3
     1901502.666      226279.763     1901746.546      227040.966
      1901842.62      227214.638
#Sta/Elev= 30
       0 2126.48    69.9 2088.41    79.9 2084.45    99.9 2080.31   129.9  2069.4
   189.8 2043.22   199.8 2042.45   209.8 2038.76   289.8 1998.61   309.7 1992.87
   389.7 1946.49   399.7  1945.1   409.6 1940.26   469.6 1897.56   479.6  1892.8
   489.6 1891.21   608.5 1887.51   628.5 1887.06   639.4    1887   649.4 1887.62
   679.4 1899.94   719.4 1908.58   729.4  1913.3   769.3 1940.41   809.2 1962.83
   829.1 1968.74   908.5 2018.87   918.4 2023.79   928.3 2025.32   997.8 2068.24
#Mann= 3 , 0 , 0
       0      .1       0   608.5    .045       0   628.5      .1       0
Bank Sta=608.5,628.5
XS Rating Curve= 0 ,0
Exp/Cntr=0.3,0.1

Type RM Length L Ch R = 1 ,3321.3  ,405.7,392.3,378.8
XS GIS Cut Line= 3
     1901460.171      226418.332     1901467.562      226693.621
      1901490.32      227463.779
#Sta/Elev= 30
       0 2077.69    39.3 2059.59      59 2055.42   127.9 2021.48   147.5 2016.42
   226.2 1974.04     236 1969.73   245.9 1968.74   285.4 1946.22   325.4 1908.63
   345.4 1907.53   365.4 1890.38   375.4 1888.18   488.3 1883.87   505.5 1882.87
   508.3 1883.21   535.6 1885.94   565.6 1891.76   625.6  1917.7   635.6 1918.19
   685.6 1948.96   725.7 1978.13   735.7 1978.78   815.7 2035.24   825.7 2035.76
   915.8 2096.93   925.8 2097.37  1005.9 2141.19  1015.9 2141.54  1045.9 2154.94
#Mann= 3 , 0 , 0
       0      .1       0   488.3    .045       0   508.3      .1       0
Bank Sta=488.3,508.3
XS Rating Curve= 0 ,0
Exp/Cntr=0.3,0.1

Type RM Length L Ch R = 1 ,2928.9  ,203.9,204.1,205.3
XS GIS Cut Line= 3
     1900859.933      226503.239     1901244.005      227172.144
     1901410.462      227477.465
#Sta/Elev= 30
       0 1988.75    39.6  1982.3    59.3 1983.14    98.9 1978.67   158.2 1968.87
     178 1969.13   217.6 1961.61     267 1944.86   276.9 1944.39   286.8 1939.04
   296.7 1938.76   385.7 1897.76   405.4 1893.04   435.1 1881.82   566.6 1874.79
   583.4 1873.98   586.6 1874.09     623 1878.13   662.6 1888.29   721.9 1921.77
   741.7 1927.98   840.9 1999.96   850.8 2001.64   930.3 2055.01   960.1  2065.9
   999.8 2085.24  1049.5 2105.28  1069.4 2110.97  1089.3 2121.95  1119.1 2134.42
#Mann= 3 , 0 , 0
       0      .1       0   566.6    .045       0   586.6      .1       0
Bank Sta=566.6,586.6
XS Rating Curve= 0 ,0
Exp/Cntr=0.3,0.1

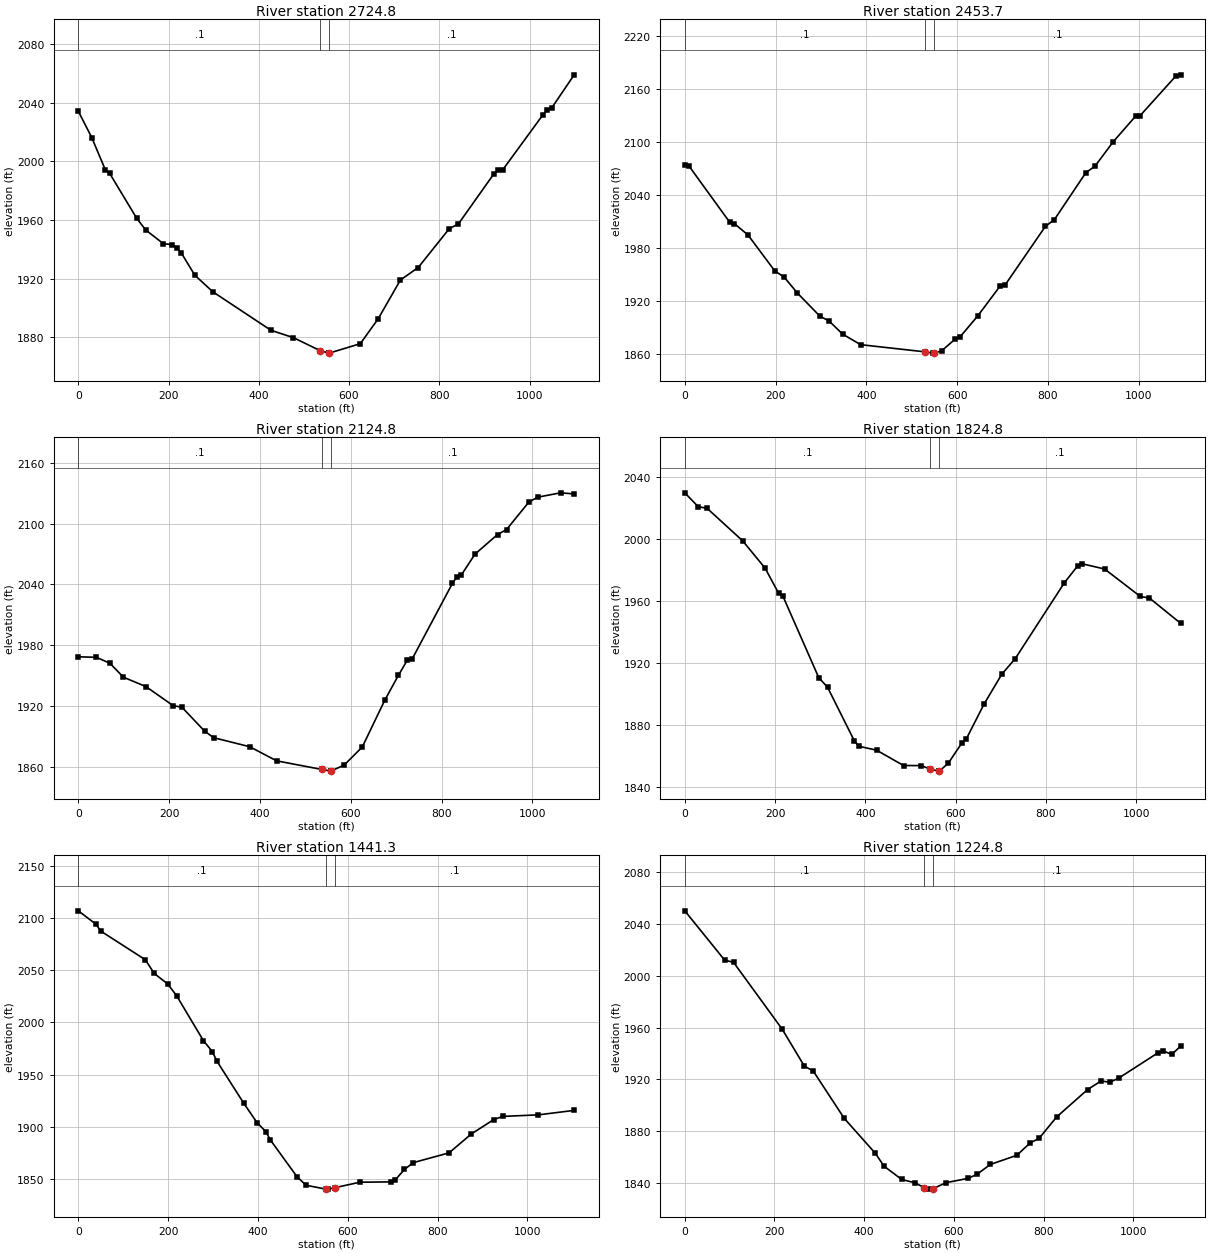
Type RM Length L Ch R = 1 ,2724.8  ,264.5,271.1,276.7
XS GIS Cut Line= 3
     1900711.496      226580.837     1900961.108      227066.413
     1901194.011      227567.912
#Sta/Elev= 30
       0 2034.24    29.8 2016.23    59.6 1994.43    69.5 1991.79     129 1961.36
   148.9  1953.3   188.6  1943.8   208.5 1943.21   218.4 1940.87   228.3 1937.48
   258.1 1922.34   297.8 1911.07   426.8 1884.74   476.5 1879.72     536 1870.83
   555.8 1869.14     556 1869.15     625 1875.59   664.5 1892.56   713.8 1919.04
   753.3 1927.58   822.4  1954.2   842.2 1957.26   921.2  1991.6   931.1 1994.27
   940.9 1994.38  1029.8 2031.85  1039.7 2035.32  1049.6 2036.69  1098.9 2059.09
#Mann= 3 , 0 , 0
       0      .1       0     536    .045       0     556      .1       0
Bank Sta=536,556
XS Rating Curve= 0 ,0
Exp/Cntr=0.3,0.1

Type RM Length L Ch R = 1 ,2453.7  ,332.4,328.9,325.2
XS GIS Cut Line= 3
     1900598.257      226634.112     1900713.663      227167.777
     1900829.068      227701.441
#Sta/Elev= 30
       0 2073.53     9.9 2072.27    99.3    2009   109.2 2007.68     139 1994.97
   198.6 1954.04   218.4 1947.59   248.2 1929.16   297.8 1903.07   317.7 1897.81
   347.4    1883   387.2 1871.03   529.8 1862.87     546 1861.48   549.8 1861.63
   565.8 1864.11   595.6  1877.4   605.6 1879.41   645.3 1903.56   694.9 1937.52
   704.8 1937.95   794.2 2004.64     814 2012.24   883.5  2065.4   903.4 2072.52
   943.1 2099.83   992.7 2128.97  1002.6 2129.53  1082.1  2174.7    1092 2175.71
#Mann= 3 , 0 , 0
       0      .1       0   529.8    .045       0   549.8      .1       0
Bank Sta=529.8,549.8
XS Rating Curve= 0 ,0
Exp/Cntr=0.3,0.1

Type RM Length L Ch R = 1 ,2124.8  ,299.8,300,302.4
XS GIS Cut Line= 3
     1900205.373      226723.583       1900394.2      227236.002
     1900585.922      227747.215
#Sta/Elev= 30
       0 1968.56    39.7 1968.05    69.5 1962.21    99.3  1948.4   148.9 1939.13
   208.5 1920.42   228.4 1918.65     278 1895.17   297.9 1888.66   377.3 1879.75
   436.9 1865.75   536.1 1857.28     556 1855.61   556.1 1855.62   585.8 1861.67
   625.5 1879.51   675.2 1925.88   704.9 1950.17   724.8 1965.38   734.7  1965.9
   824.1  2041.2     834  2047.6   843.9 2049.56   873.7    2070   923.3 2089.36
   943.2 2094.27   992.8 2121.69  1012.7 2126.34  1062.3 2130.55  1092.1 2129.46
#Mann= 3 , 0 , 0
       0      .1       0   536.1    .045       0   556.1      .1       0
Bank Sta=536.1,556.1
XS Rating Curve= 0 ,0
Exp/Cntr=0.3,0.1

Type RM Length L Ch R = 1 ,1824.8  ,392.7,383.5,372.2
XS GIS Cut Line= 3
     1899927.028      226820.925     1900120.841      227339.722
     1900267.795      227864.305
#Sta/Elev= 30
       0 2029.94    29.7 2020.98    49.4 2019.93   128.6 1998.79     178 1981.21
   207.7 1965.11   217.6    1963   296.7 1910.53   316.5 1904.13   375.8  1869.5
   385.7 1866.11   425.2 1863.52   484.6 1853.65   524.2 1853.58   543.8 1851.28
   563.7 1850.02   563.8 1850.04   583.5 1854.98   613.2 1867.92   623.2 1870.53
   662.8 1893.22   702.4 1912.69   732.1 1922.72   841.1 1971.82   870.8 1982.81
   880.7 1984.04   930.2 1980.68  1009.4 1962.92  1029.3 1961.96  1098.6 1945.57
#Mann= 3 , 0 , 0
       0      .1       0   543.8    .045       0   563.8      .1       0
Bank Sta=543.8,563.8
XS Rating Curve= 0 ,0
Exp/Cntr=0.3,0.1

Type RM Length L Ch R = 1 ,1441.3  ,222.5,216.4,212.7
XS GIS Cut Line= 2
      1899432.58      227081.186     1900168.159      227904.641
#Sta/Elev= 30
       0 2107.01    39.8 2093.98    49.7 2087.67   149.2 2060.12   169.1 2046.94
     199 2036.88   218.8 2025.67   278.5  1982.6   298.4 1972.08   308.4 1963.05
     368 1922.83   397.9 1904.02   417.8 1895.24   427.7 1887.35   487.4 1851.92
   507.3 1843.93   550.9 1840.29     557 1840.24   570.9 1841.58   626.7 1846.85
   696.3 1847.19   706.3  1849.3   726.2 1859.13     746 1865.64   825.6    1875
   875.4 1893.16   925.1  1906.9     945 1909.94  1024.6 1911.44  1104.2 1915.72
#Mann= 3 , 0 , 0
       0      .1       0   550.9    .045       0   570.9      .1       0
Bank Sta=550.9,570.9
XS Rating Curve= 0 ,0
Exp/Cntr=0.3,0.1

Type RM Length L Ch R = 1 ,1224.8  ,219.9,215.1,208
XS GIS Cut Line= 3
     1899189.994      227321.412      1899638.22      227628.074
     1900071.013      227987.345
#Sta/Elev= 30
       0  2050.1    88.9 2012.04   108.6  2010.4   217.2 1958.76   266.6 1930.27
   286.4 1926.48   355.5 1889.99   424.6  1863.1   444.4 1853.03   483.8 1842.79
   513.5 1840.24   533.1  1836.6   543.1 1835.36   553.1 1835.61   582.6 1840.37
   631.9 1843.66   651.6 1846.82   681.2 1854.39   740.4 1861.47   770.1 1871.03
   789.8 1874.46   829.3  1891.1   898.3 1912.22     928 1918.82   947.7 1917.85
   967.4 1920.99  1056.2 1940.77  1066.1 1942.12  1085.8 1939.28  1105.6 1945.67
#Mann= 3 , 0 , 0
       0      .1       0   533.1    .045       0   553.1      .1       0
Bank Sta=533.1,553.1
XS Rating Curve= 0 ,0
Exp/Cntr=0.3,0.1

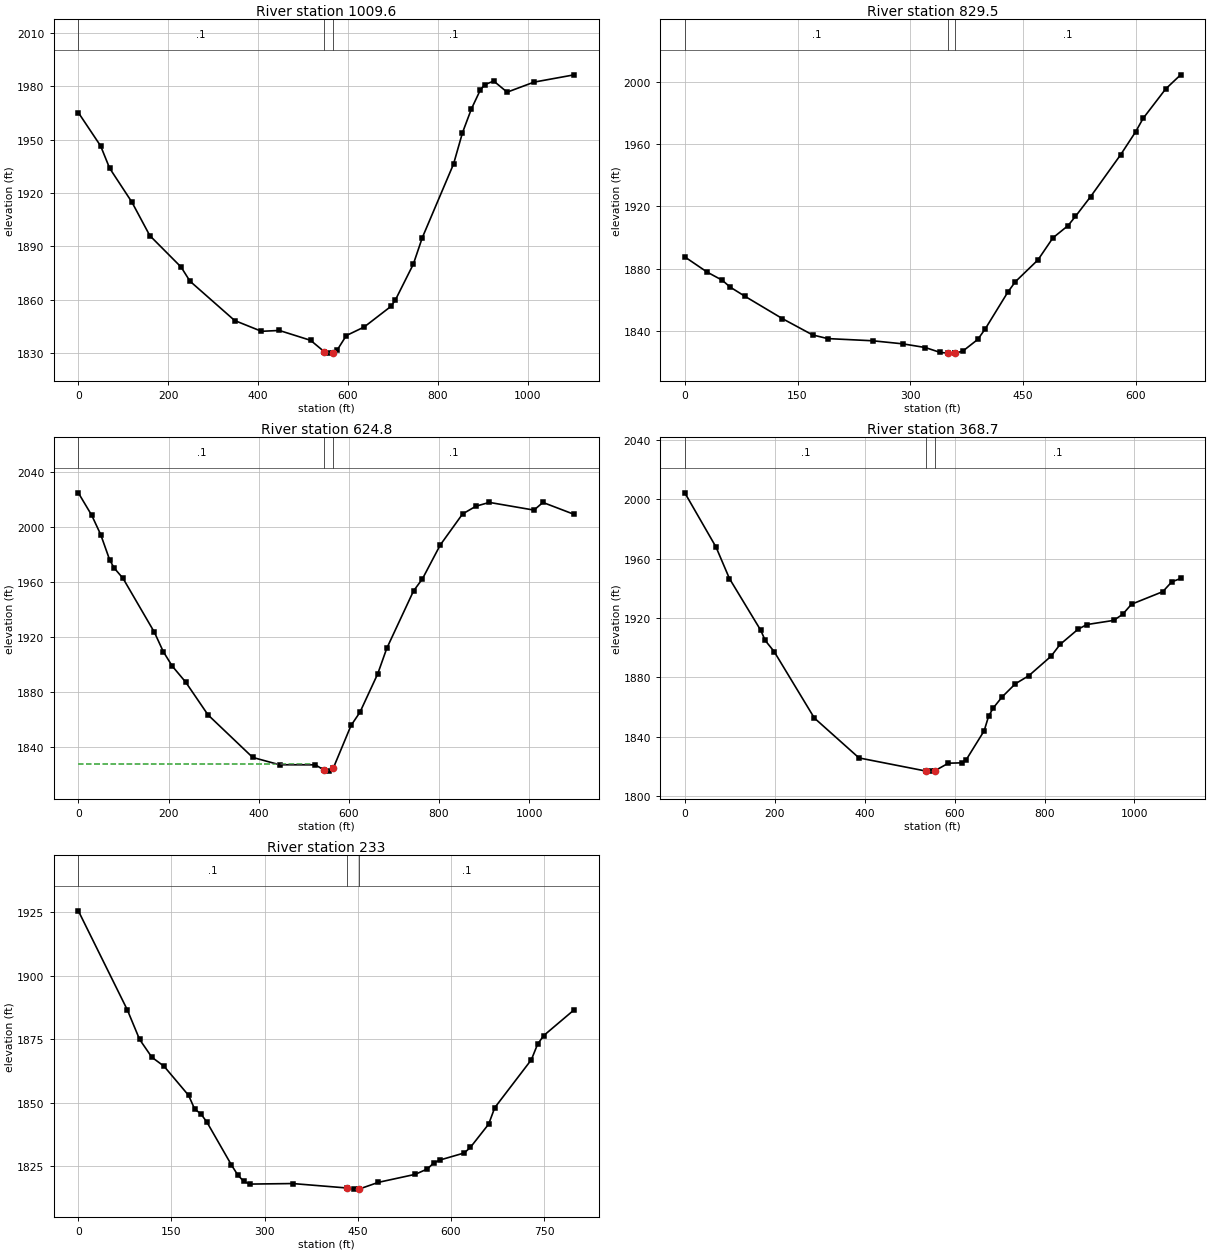
Type RM Length L Ch R = 1 ,1009.6  ,173.3,180.2,187
XS GIS Cut Line= 2
     1899025.969      227595.967      1900038.81      228034.701
#Sta/Elev= 30
       0 1965.24    49.7 1946.46    69.6    1934   119.3 1914.87   159.1 1896.08
   228.7 1878.41   248.6 1870.44     348 1848.34   407.7 1842.28   447.5 1842.75
   517.1  1837.2     547 1830.91   556.9 1830.01     567 1830.21   576.8 1831.96
   596.6 1839.88   636.4 1844.71   696.1 1856.33     706 1859.98   745.8 1880.05
   765.7  1894.9   835.3 1936.32   855.2 1953.93   875.1 1967.33     895 1977.99
   904.9 1980.95   924.8 1982.95   954.6 1976.71  1014.3 1982.35  1103.8 1986.46
#Mann= 3 , 0 , 0
       0      .1       0     547    .045       0     567      .1       0
Bank Sta=547,567
XS Rating Curve= 0 ,0
Exp/Cntr=0.3,0.1

Type RM Length L Ch R = 1 ,829.5   ,201.3,204.7,206.6
XS GIS Cut Line= 2
     1899201.969      227728.958     1899698.043      228164.062
#Sta/Elev= 30
       0 1887.63      30 1877.82      50 1872.65      60  1868.4      80 1862.41
     130 1848.05     170 1837.66     190  1835.3   249.9  1833.9   289.9 1831.94
   319.9 1829.58   339.9 1826.42   349.9    1826   359.3 1825.98   359.9 1825.98
   369.9 1827.25   389.9 1834.78   399.9 1841.58   429.9  1865.1   439.9 1871.74
   469.9 1885.68   489.9 1899.86   509.9 1907.64   519.9 1913.62   539.9 1926.17
   579.9 1953.04   599.9 1967.77   609.9  1976.4   639.9 1995.25   659.8  2004.3
#Mann= 3 , 0 , 0
       0      .1       0   349.9    .045       0   359.9      .1       0
Bank Sta=349.9,359.9
XS Rating Curve= 0 ,0
Exp/Cntr=0.3,0.1

Type RM Length L Ch R = 1 ,624.8   ,262.6,256.1,250.9
XS GIS Cut Line= 3
     1898961.576      227688.753     1899326.529      228107.284
     1899706.153      228497.428
#Sta/Elev= 30
       0 2024.98    29.8 2008.55    49.6 1994.57    69.4 1976.22    79.3 1970.28
    99.2 1962.64   168.6 1923.46   188.4 1909.32   208.2 1898.79     238 1887.14
   287.6 1863.23   386.7 1832.24   446.2  1826.9   525.6 1826.83   545.3    1823
   555.3 1822.25   565.3 1824.29   604.8 1855.49   624.6 1865.14   664.2 1893.26
     684 1911.64   743.4 1953.48   763.2 1962.32   802.7 1986.98   852.2 2009.58
   881.9 2015.24   911.6    2018  1010.6  2012.4  1030.4 2017.98  1099.7 2009.28
#Mann= 3 , 0 , 0
       0      .1       0   545.3    .045       0   565.3      .1       0
#XS Ineff= 2 , 0
          515.41 1827.26
Permanent Ineff=
       F       F
Bank Sta=545.3,565.3
XS Rating Curve= 0 ,0
Exp/Cntr=0.3,0.1

Type RM Length L Ch R = 1 ,368.7   ,137.1,135.7,134.3
XS GIS Cut Line= 2
     1898694.962      227976.734     1899608.623      228594.011
#Sta/Elev= 30
       0 2004.39    69.5 1967.78    99.3 1946.57   168.9  1911.7   178.8 1904.86
   198.7 1897.36   288.1 1852.56   387.4 1825.67   536.8 1816.78   546.4 1816.77
   556.8 1817.14   586.1 1822.12   615.9 1822.36   625.8 1824.43   665.6  1843.9
   675.5 1853.69   685.4 1859.13   705.3 1866.68   735.1 1875.66   764.9 1881.07
   814.6 1894.26   834.4 1902.14   874.2 1912.35     894 1915.58   953.6 1918.38
   973.5 1922.43   993.4  1929.3  1062.9 1937.76  1082.8 1944.33  1102.6 1946.66
#Mann= 3 , 0 , 0
       0      .1       0   536.8    .045       0   556.8      .1       0
Bank Sta=536.8,556.8
XS Rating Curve= 0 ,0
Exp/Cntr=0.3,0.1

Type RM Length L Ch R = 1 ,233     ,237.7,232.9,226.7
XS GIS Cut Line= 3
     1898683.723      228161.291     1899217.211      228479.998
     1899393.193      228499.398
#Sta/Elev= 30
       0 1925.64    78.9 1886.57    98.6 1874.93   118.4 1867.87   138.1  1864.3
   177.6 1852.82   187.4  1847.4   197.3 1845.56   207.2 1842.22   246.6 1825.36
   256.5 1821.52   266.3 1818.89   276.2 1817.83   345.2 1818.04   432.1  1816.3
   443.9 1815.84   452.1 1815.86   483.3 1818.52   542.5 1821.67   562.2 1823.81
   572.1 1826.12     582  1827.3   621.4  1830.1   631.3 1832.29   660.8 1841.48
   670.6 1847.97   729.6  1866.9   739.5 1872.96   749.3 1876.39   798.5 1886.59
#Mann= 3 , 0 , 0
       0      .1       0   432.1    .045       0   452.1      .1       0
Bank Sta=432.1,452.1
XS Rating Curve= 0 ,0
Exp/Cntr=0.3,0.1

Chan Stop Cuts=-1
Use User Specified Reach Order=0
Composite Channel Slope=5